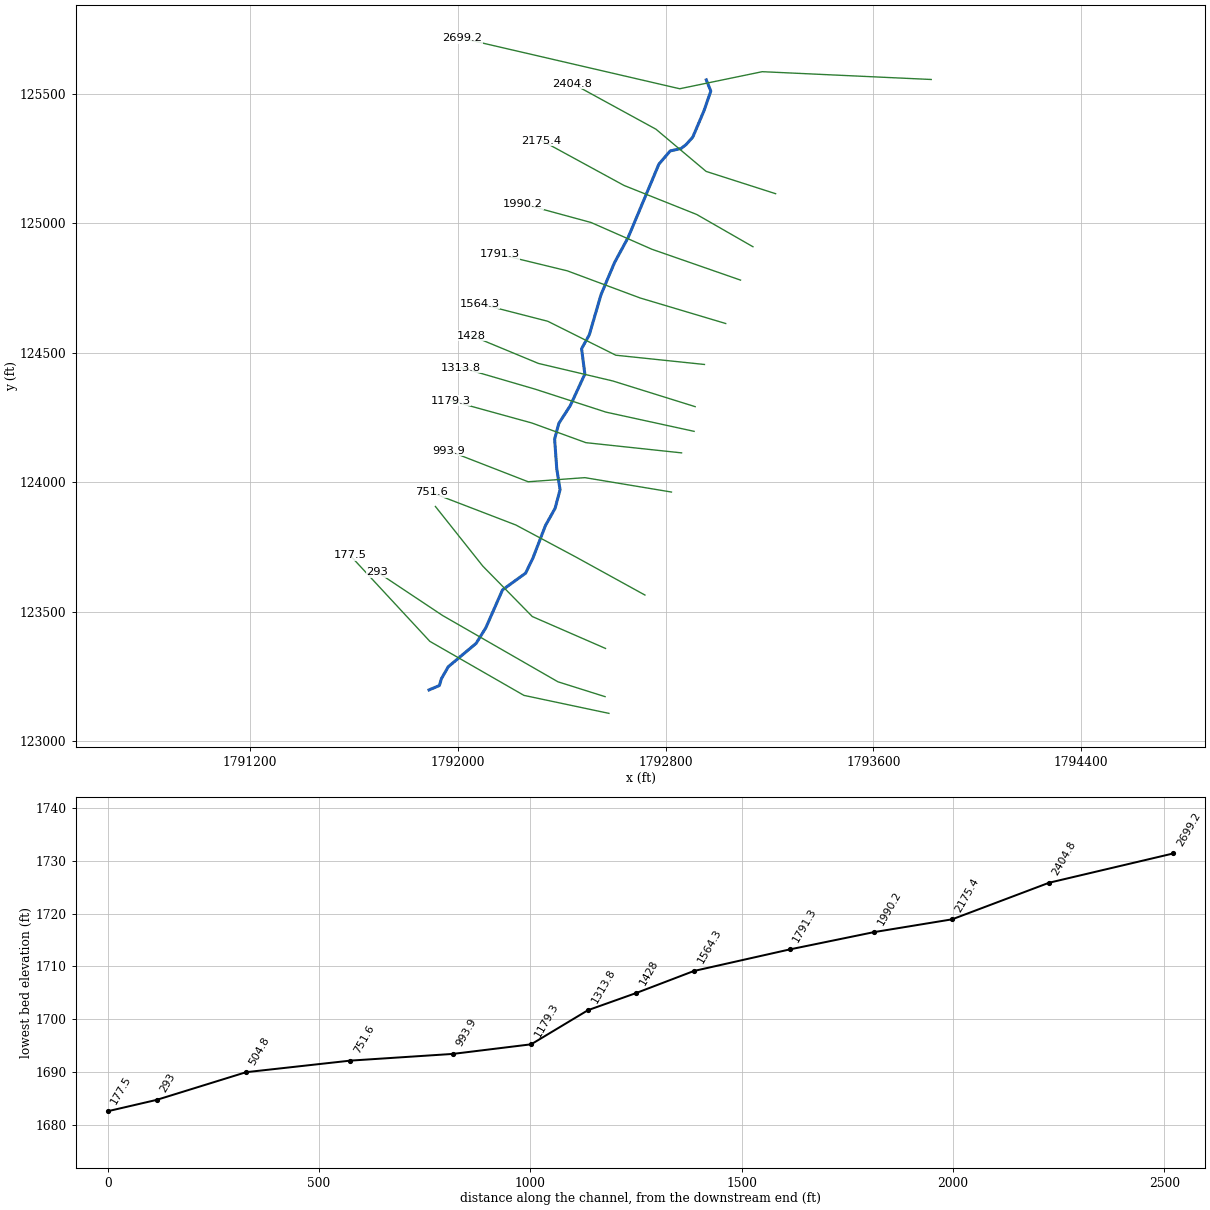
--- Split Fork Trib 1.prj (project) ---

Proj Title=Split Fork Trib 1
Current Plan=p01
Default Exp/Contr=0,0
English Units
Geom File=g01
Flow File=f01
Plan File=p01
BEGIN DESCRIPTION:
END DESCRIPTION:
DSS Export Rating Curves= 0
DSS Export Rating Curve Sorted= 0
DSS Export Volume Flow Curves= 0
DXF OffsetX= 0
DXF OffsetY= 0
DXF ScaleX= 0
DXF ScaleY= 0

--- Split Fork Trib 1.p01 (plan) ---

Plan Title=Floodplain
Program Version=4.00
Geom File=g01
Flow File=f01
K Sum by GR=0
Std Step Tol=0.01
Critical Tol=0.01
Num of Std Step Trials=20
Max Error Tol=0.3
Flow Tol Ratio=0.001
Split Flow NTrial=30
Split Flow Tol=0.02
Split Flow Ratio=0.02
Log Output Level=0
Friction Slope Method=1
Unsteady Friction Slope Method=2
Unsteady Bridges Friction Slope Method=1
Global Log Level=0
CheckData=False
Run HTab=0
Run UNet=0
Run PostProcess=0
UNET Theta=0
UNET Theta Warmup=0
UNET ZTol=0
UNET ZSATol=0
UNET MxIter=0
UNET MaxInSteps=0
UNET DtIC=0
UNET DtMin=0
UNET MaxCRTS=0
UNET WFStab=0
UNET SFStab=0
UNET WFX=0
UNET SFX=0
UNET DSS MLevel=0
UNET DZMax Abort=0
UNET Convert EG Bridges=0
UNET Use Existing IB Tables=0
UNET Froude Limit=0
UNET Froude Power=0
Write IC File=0
Echo Input=False
Echo Output=False
Write Detailed=0

--- Split Fork Trib 1.f01 (steady flow) ---

Flow Title=NFF Regression Equation
Program Version=4.00
Number of Profiles=1
Profile Names=P100yr
River Rch & RM=Split Fork Tr...,Main      ,2699.2
581.0772
River Rch & RM=Split Fork Tr...,Main      ,1990.2
602.5506
River Rch & RM=Split Fork Tr...,Main      ,293
665.0175
Boundary for River Rch & Prof#=Split Fork Tr...,Main      ,1
Up Type=0
Dn Type=3
Dn Slope=0.017417

--- Split Fork Trib 1.g01 (geometry) ---

Geom Title=USGS 10m DEM
Program Version=4.00

River Reach=Split Fork Tr...,Main
Reach XY= 30
     1792956.637       125552.73     1792974.134      125509.362
     1792947.449      125432.343     1792904.576      125331.684
     1792878.604      125302.628     1792859.456      125287.917
     1792817.464      125278.282     1792774.092      125227.297
     1792655.806      124944.544      1792603.53       124847.96
     1792551.337         124724.     1792506.198      124568.877
      1792476.54      124515.493     1792489.126      124417.574
     1792433.318      124296.315     1792389.047      124227.578
     1792372.736      124166.996     1792380.892      124052.822
     1792393.707       123971.27     1792374.385      123899.268
     1792337.478      123833.361     1792289.366      123708.139
     1792261.026      123649.482     1792172.052      123584.894
     1792108.123      123439.241     1792070.557      123378.607
     1791963.129      123288.315     1791936.766      123242.181
     1791928.858      123215.818     1791889.159      123199.013

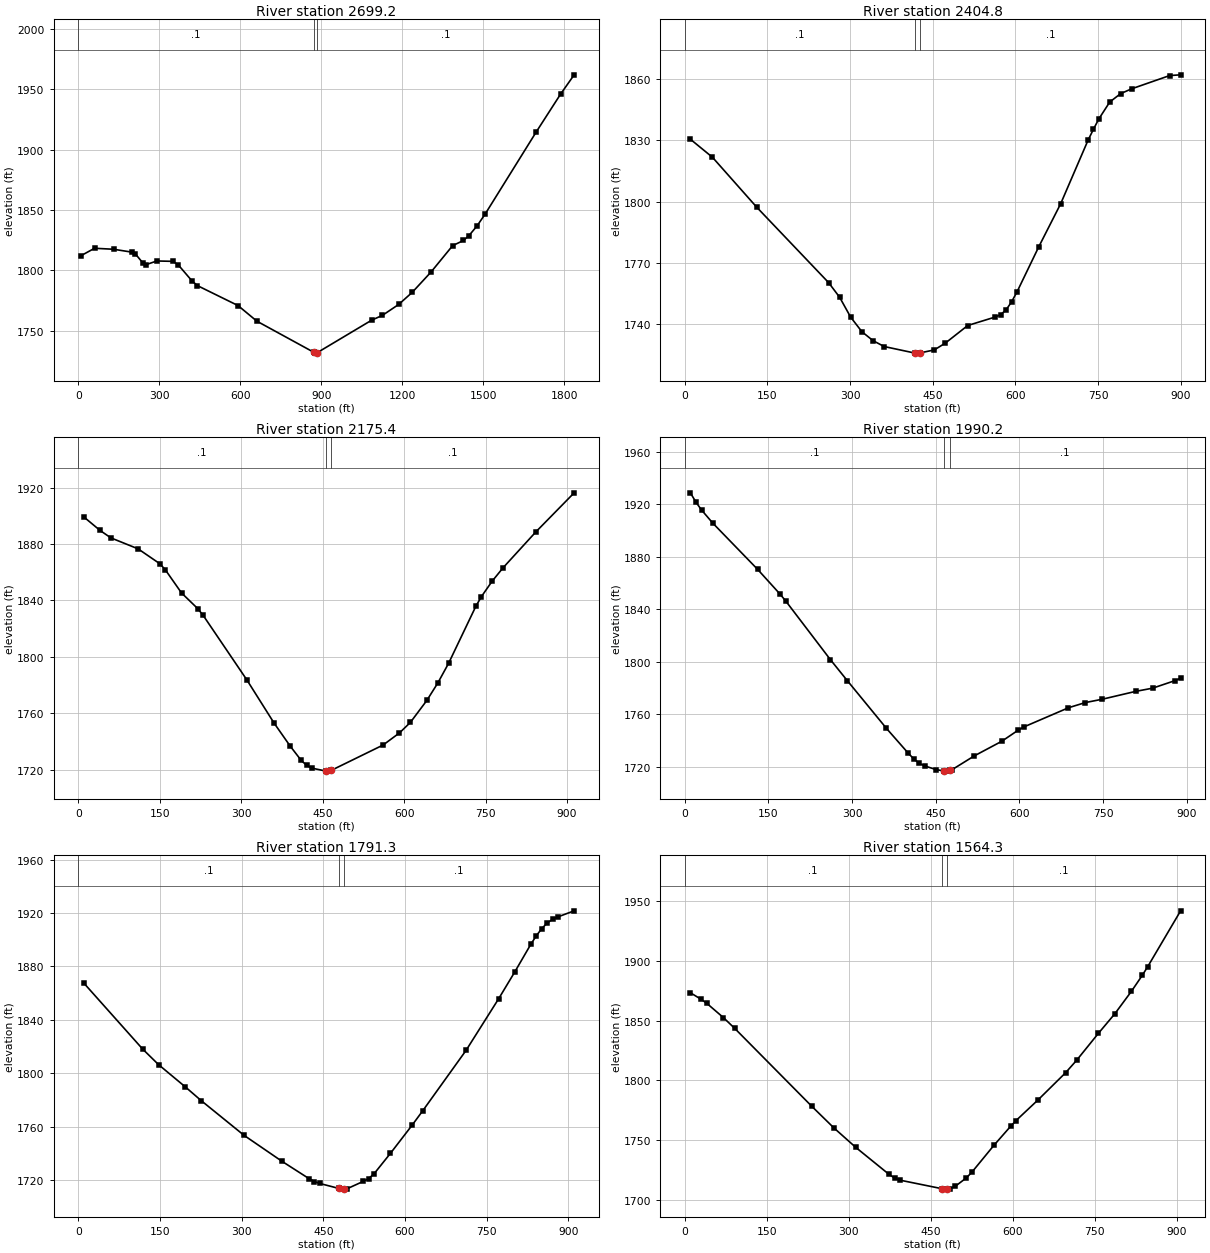
Type RM Length L Ch R = 1 ,2699.2  ,311.9,294.4,277.7
XS GIS Cut Line= 4
     1793822.923      125554.133     1793172.251       125584.24
     1792854.388      125518.409     1792016.844      125712.909
#Sta/Elev= 30
      10 1812.13    60.1 1818.25   130.3 1817.43   200.4 1814.97   210.4  1813.8
   240.5 1805.68   250.5 1804.66   290.6 1807.73   350.7 1807.42   370.8 1804.27
   420.9 1791.22   440.9 1787.32   591.2 1770.81   661.2 1757.86   872.6 1732.02
   877.6 1731.42   882.6 1731.55    1086  1758.7  1125.9  1762.7  1185.9  1771.7
  1235.9 1781.67  1305.9 1798.58  1385.9 1820.43  1425.9 1824.69  1445.9 1828.63
  1475.9 1836.67  1505.9 1846.45  1695.8 1914.72  1785.8 1945.99  1835.8 1961.87
#Mann= 3 , 0 , 0
       0      .1       0   872.6    .045       0   882.6      .1       0
Bank Sta=872.6,882.6
XS Rating Curve= 0 ,0
Exp/Cntr=0.3,0.1

Type RM Length L Ch R = 1 ,2404.8  ,223.8,229.3,234.1
XS GIS Cut Line= 4
     1793223.543      125113.529     1792956.098      125199.482
     1792762.793      125362.379      1792441.57      125538.256
#Sta/Elev= 30
      10 1830.49    50.2 1821.64   130.4 1797.26   260.9 1760.37   280.9 1753.23
   301.1 1743.43   321.4 1736.34   341.6 1731.97   361.8 1729.09   417.5 1725.89
   422.5 1725.86   427.5 1726.01   452.8 1727.42     473 1730.79   513.5 1739.37
   563.4 1743.52   573.3 1744.68   583.2 1747.05   593.1 1750.94     603 1755.84
   642.6 1777.95   682.2 1798.92   731.7 1829.88   741.6 1835.32   751.5 1840.41
   771.3 1848.67     791 1852.76   810.8  1855.1   880.1 1861.61   899.9 1861.96
#Mann= 3 , 0 , 0
       0      .1       0   417.5    .045       0   427.5      .1       0
Bank Sta=417.5,427.5
XS Rating Curve= 0 ,0
Exp/Cntr=0.3,0.1

Type RM Length L Ch R = 1 ,2175.4  ,185.9,185.2,184.6
XS GIS Cut Line= 4
     1793136.436      124908.799     1792919.735      125033.367
      1792640.04      125145.285     1792322.413       125318.72
#Sta/Elev= 30
      10 1899.29      40 1889.68      60 1884.39     110 1876.63     150 1866.09
     160 1861.87     190 1845.36     220 1834.17     230 1829.36   310.2 1783.74
   360.4 1753.06   390.5  1736.5   410.6 1726.48   420.7 1722.95   430.7    1721
   455.8 1718.99   460.8 1718.93   465.8 1719.47   561.3 1737.46   591.4 1746.04
   611.5 1753.49   641.7 1769.04   661.8 1781.32   681.9 1795.45   732.2 1835.98
   742.2 1842.69   762.3  1853.8   782.4 1863.29   842.7  1888.7   913.1 1916.36
#Mann= 3 , 0 , 0
       0      .1       0   455.8    .045       0   465.8      .1       0
Bank Sta=455.8,465.8
XS Rating Curve= 0 ,0
Exp/Cntr=0.3,0.1

Type RM Length L Ch R = 1 ,1990.2  ,197.8,198.9,200.1
XS GIS Cut Line= 4
     1793088.583      124780.099     1792747.214      124899.182
     1792513.019      125002.386     1792251.038      125073.835
#Sta/Elev= 30
      10 1928.61    20.1 1921.43    30.1 1915.49    50.2 1905.51   130.6 1870.26
   170.7 1851.45   180.8 1846.25   261.1 1801.44   291.2 1785.55   361.5 1749.11
   400.9 1730.04   410.8 1725.72   420.6 1722.37   430.4 1720.42   450.1 1717.73
   464.8 1716.57   469.8  1716.5   474.8 1717.12   479.7 1717.74     519  1728.1
   568.3 1739.25   597.8 1747.72   607.6 1750.12   687.9  1764.8     718 1768.74
   748.2 1771.27   808.6  1777.3   838.7 1779.72     879 1785.49     889 1787.34
#Mann= 3 , 0 , 0
       0      .1       0   464.8    .045       0   474.8      .1       0
Bank Sta=464.8,474.8
XS Rating Curve= 0 ,0
Exp/Cntr=0.3,0.1

Type RM Length L Ch R = 1 ,1791.3  ,229.1,227,224.8
XS GIS Cut Line= 4
     1793031.473      124612.646     1792701.938      124711.198
     1792421.723      124815.824     1792161.355      124879.163
#Sta/Elev= 30
     9.8 1867.67   117.9 1818.25   147.4 1806.47   196.5 1789.82     226 1779.43
   304.6 1753.48   373.9 1734.14   423.7 1721.13   433.7 1718.92   443.7 1717.45
   478.5 1713.77   483.5 1713.23   488.5 1713.35   493.5 1713.47   523.4 1719.01
   533.4 1721.13   543.4 1724.75   573.3 1739.96   613.2 1761.08   633.1 1772.09
   712.5 1817.22   772.1 1855.71   801.9  1875.9   831.6 1896.77   841.6 1903.03
   851.5 1908.39   861.4 1912.51   871.3  1915.3   881.3 1917.15     911 1921.66
#Mann= 3 , 0 , 0
       0      .1       0   478.5    .045       0   488.5      .1       0
Bank Sta=478.5,488.5
XS Rating Curve= 0 ,0
Exp/Cntr=0.3,0.1

Type RM Length L Ch R = 1 ,1564.3  ,131.5,136.3,141.1
XS GIS Cut Line= 4
     1792949.654      124454.608     1792608.285      124490.333
     1792346.304      124621.323     1792084.324      124688.803
#Sta/Elev= 30
    10.1 1873.28    30.3 1867.67    40.4 1864.34    70.7 1852.45    90.9 1843.65
   232.2 1778.37   272.6 1760.32   312.9 1743.93   373.5 1721.47   383.6  1718.4
   393.7 1716.62   469.5 1709.57   474.5 1709.14   479.5 1709.26   484.6 1709.38
   494.7 1711.54   514.9 1718.56     525 1723.31   565.4 1745.81   595.7 1761.57
   605.8 1766.47   646.2 1783.81   696.3 1806.39   716.3  1816.7   756.4 1839.37
   786.4  1855.7   816.5 1874.31   836.5 1887.75   846.5 1895.04   906.7 1941.72
#Mann= 3 , 0 , 0
       0      .1       0   469.5    .045       0   479.5      .1       0
Bank Sta=469.5,479.5
XS Rating Curve= 0 ,0
Exp/Cntr=0.3,0.1

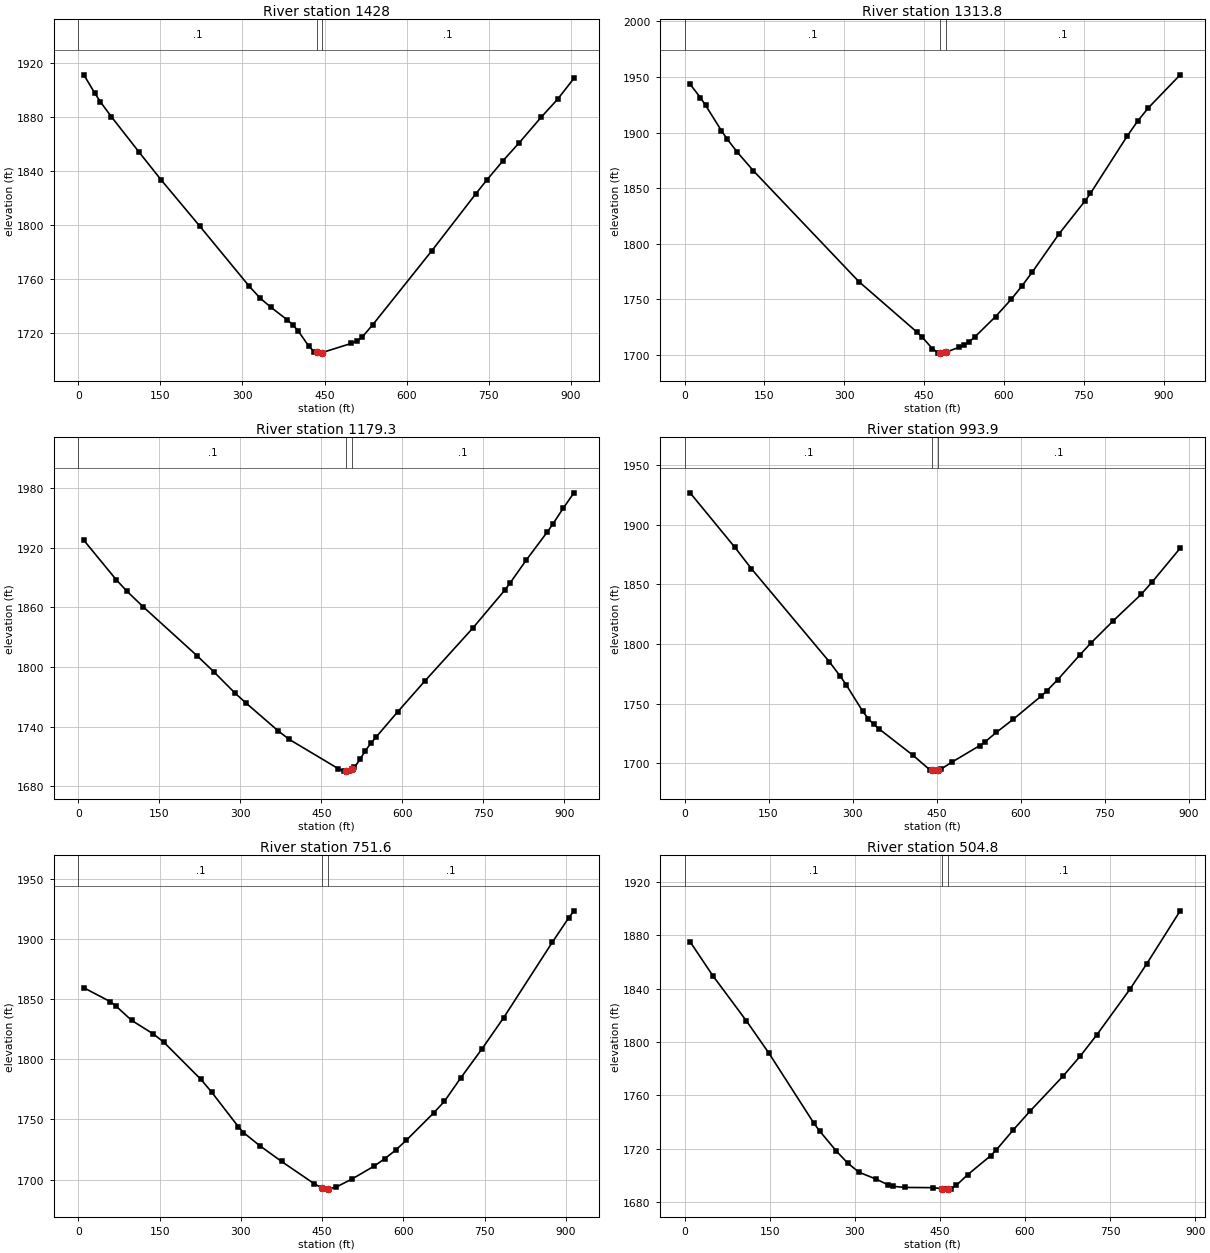
Type RM Length L Ch R = 1 ,1428    ,115.8,114.1,112.5
XS GIS Cut Line= 4
     1792913.929      124291.863     1792596.377      124391.098
      1792310.58      124458.578     1792052.568      124565.752
#Sta/Elev= 30
    10.1 1911.16    30.2 1897.53    40.3 1891.14    60.5 1880.09   110.9 1853.94
   151.2 1833.38   221.8 1799.12   312.5 1754.42   332.7 1745.54   352.3 1738.84
   381.6 1729.69   391.4  1726.1   401.2 1721.71   420.8 1710.36   430.6 1706.14
   435.4 1705.57   440.4 1704.97   445.4 1705.35   499.1  1712.2   508.9 1713.87
   518.7 1716.82   538.3 1726.13   646.3 1780.96   726.1 1822.86   746.1 1833.02
     776 1847.47     806 1860.95   845.9 1879.79   875.8 1893.06   905.7 1908.55
#Mann= 3 , 0 , 0
       0      .1       0   435.4    .045       0   445.4      .1       0
Bank Sta=435.4,445.4
XS Rating Curve= 0 ,0
Exp/Cntr=0.3,0.1

Type RM Length L Ch R = 1 ,1313.8  ,135.2,134.5,133.9
XS GIS Cut Line= 4
      1792909.96      124196.597     1792570.793      124270.684
     1792298.174      124359.227     1792012.874        124442.7
#Sta/Elev= 30
     9.9 1943.76    29.8 1931.33    39.7 1924.33    69.4 1901.56    79.4 1894.53
    99.2  1882.3   128.9 1865.84   327.3 1766.08   436.1 1720.82     446 1716.35
   465.8 1705.63   475.7 1702.18   480.5 1701.96   485.5 1701.72   490.5 1702.48
   515.2 1706.87   525.1 1709.03     535  1712.1   544.8 1716.01   584.4 1734.62
     614 1750.25   633.8 1762.05   653.6 1774.78   703.2 1808.71   752.7 1838.72
   762.6 1845.34     832 1897.11   851.8 1910.65   871.6 1922.32   931.1 1951.87
#Mann= 3 , 0 , 0
       0      .1       0   480.5    .045       0   490.5      .1       0
Bank Sta=480.5,490.5
XS Rating Curve= 0 ,0
Exp/Cntr=0.3,0.1

Type RM Length L Ch R = 1 ,1179.3  ,176.9,185.4,193.9
XS GIS Cut Line= 4
     1792861.513      124113.556     1792493.172      124152.933
     1792285.359      124228.743      1791971.23      124315.504
#Sta/Elev= 30
      10 1927.73    70.1 1887.94    90.1 1876.26   120.1  1860.6   220.3 1811.13
   250.3 1795.51   290.3 1773.68   310.4 1763.82   370.4 1735.56   390.5 1727.19
     481  1697.8   491.1 1695.36   496.2 1695.31   501.2 1695.25   506.2 1697.12
   511.2 1698.99   521.3 1706.97   531.3 1715.73   541.4 1723.15   551.4 1729.64
   591.6 1755.17     641 1785.62   729.9 1838.97   789.2 1877.23     799 1884.33
   828.7 1907.28   868.2 1935.95     878 1943.58   897.8 1959.93   917.5 1975.35
#Mann= 3 , 0 , 0
       0      .1       0   496.2    .045       0   506.2      .1       0
Bank Sta=496.2,506.2
XS Rating Curve= 0 ,0
Exp/Cntr=0.3,0.1

Type RM Length L Ch R = 1 ,993.9   ,253.8,242.3,230.9
XS GIS Cut Line= 4
     1792822.633      123962.402     1792489.203      124017.974
     1792270.886      124002.096     1791965.241      124121.178
#Sta/Elev= 30
     9.9 1926.62    89.5 1881.15   119.3 1863.08   258.5 1785.07   278.4 1772.72
   288.3 1765.99   318.1 1743.57   328.1 1737.28     338 1732.51     348 1728.54
   407.7 1706.77   437.5 1694.71   442.5 1694.07   447.5 1693.43   452.5  1694.2
   457.4 1694.97   477.3 1700.96   527.1 1714.84     537 1718.14   556.9 1725.97
   586.7 1736.81   636.4 1756.17   646.4 1760.49   666.3 1770.08     706 1790.91
   725.9 1800.93   765.7 1819.52   815.4 1841.63   835.2 1852.07   884.9 1880.23
#Mann= 3 , 0 , 0
       0      .1       0   442.5    .045       0   452.5      .1       0
Bank Sta=442.5,452.5
XS Rating Curve= 0 ,0
Exp/Cntr=0.3,0.1

Type RM Length L Ch R = 1 ,751.6   ,253.1,246.7,240.4
XS GIS Cut Line= 4
     1792720.442      123565.048     1792453.478       123712.33
     1792223.253      123835.381     1791897.635      123960.744
#Sta/Elev= 30
     9.8 1859.41      59 1847.81    68.8 1844.44    98.4 1832.27   137.7 1821.21
   157.4 1814.36   226.2 1783.31   245.9 1772.83   295.1 1744.14   304.9 1739.11
     335  1728.2   375.2 1715.13   435.4 1696.66   450.5 1692.93   455.5 1692.16
   460.5 1692.22   475.6 1693.77   505.7 1700.68   545.9 1711.22   565.9 1717.47
   585.9 1724.57   605.8 1732.89   655.7  1755.3   675.6 1764.92   705.5 1784.21
   745.4 1808.74   785.3 1834.59     875 1897.12   904.9 1917.17   914.9 1923.22
#Mann= 3 , 0 , 0
       0      .1       0   450.5    .045       0   460.5      .1       0
Bank Sta=450.5,460.5
XS Rating Curve= 0 ,0
Exp/Cntr=0.3,0.1

Type RM Length L Ch R = 1 ,504.8   ,206.2,211.8,217.4
XS GIS Cut Line= 4
     1792568.591      123359.053     1792286.763      123482.104
     1792096.232      123676.605     1791913.639       123906.83
#Sta/Elev= 30
     9.9 1874.87    49.6 1849.72   109.1 1815.75   148.8 1791.59   228.2  1739.1
   238.1 1733.43   267.8  1718.3   287.7  1709.4   307.5  1702.6   337.8 1697.44
   357.9 1693.35     368 1692.07   388.2 1691.24   438.6 1691.06   453.8 1690.31
   458.8 1689.97   463.8 1690.12   468.9 1690.28     479 1692.78   499.1 1700.78
   539.5 1714.94   549.5  1719.3   579.8 1734.43   609.2 1748.38   667.9 1774.83
   697.3 1789.37   726.7 1805.36   785.5 1839.72   814.9 1858.62   873.6 1898.09
#Mann= 3 , 0 , 0
       0      .1       0   453.8    .045       0   463.8      .1       0
Bank Sta=453.8,463.8
XS Rating Curve= 0 ,0
Exp/Cntr=0.3,0.1

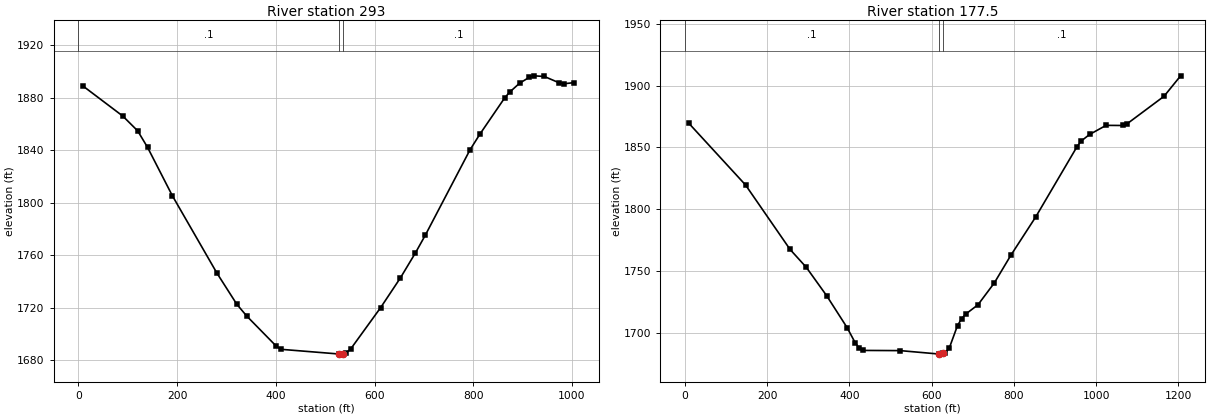
Type RM Length L Ch R = 1 ,293     ,115.2,115.6,115.9
XS GIS Cut Line= 4
     1792567.102      123172.987     1792385.552      123230.306
     1791941.425      123486.074     1791690.581      123653.297
#Sta/Elev= 30
      10 1888.88    90.2  1866.1   120.2 1854.88   140.3 1842.24   190.4 1805.47
   280.8 1746.43     321 1722.74   341.1 1713.75   401.4 1690.62   411.5 1688.36
   527.1 1684.84   532.1 1684.72   537.1 1685.09   542.1 1685.46   552.2  1688.9
   612.5 1720.23   652.6 1742.92   682.8 1761.83   702.9 1775.37   793.3 1840.33
   813.4 1852.33   863.7 1880.02   873.7 1884.37   893.8 1891.16   913.9 1895.77
     924 1896.81   944.1  1896.3   974.2 1891.45   984.3 1890.78  1004.4 1891.65
#Mann= 3 , 0 , 0
       0      .1       0   527.1    .045       0   537.1      .1       0
Bank Sta=527.1,537.1
XS Rating Curve= 0 ,0
Exp/Cntr=0.3,0.1

Type RM Length L Ch R = 1 ,177.5   ,190.2,177.5,164.5
XS GIS Cut Line= 4
     1792581.988      123108.484     1792254.512      123177.949
     1791892.304      123386.342     1791584.675       123718.78
#Sta/Elev= 30
     9.8 1869.42   147.7 1819.48     256  1767.3   295.4 1752.84   344.7 1729.97
   394.5 1704.11   414.4 1691.72   424.3 1687.32   434.3 1685.57   523.8 1685.41
   618.3 1682.64   623.3 1682.57   628.3 1683.08   633.2 1683.57   643.2 1687.59
   663.1  1705.7     673 1711.22     683 1714.97   712.8  1722.5   752.6 1740.21
   792.9 1762.64   853.3 1793.64   953.9  1850.6     964 1855.11   984.1 1860.34
  1024.4 1867.74  1064.7 1867.63  1074.7 1868.82  1165.3 1891.29  1205.6 1907.83
#Mann= 3 , 0 , 0
       0      .1       0   618.3    .045       0   628.3      .1       0
Bank Sta=618.3,628.3
XS Rating Curve= 0 ,0
Exp/Cntr=0.3,0.1

Chan Stop Cuts=-1
Use User Specified Reach Order=0